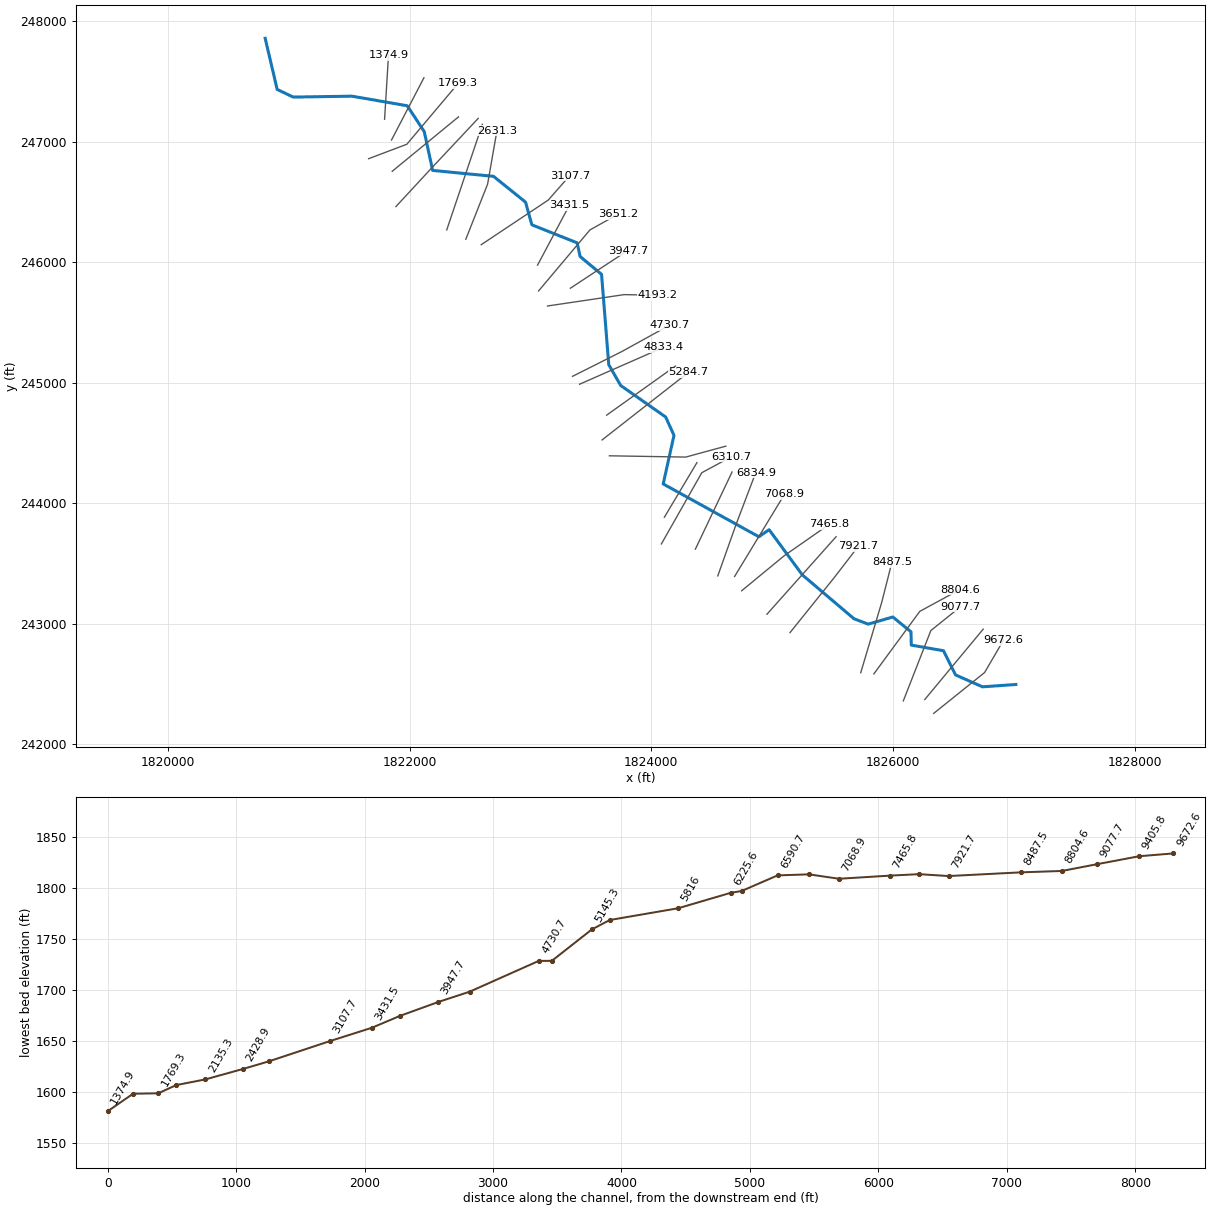
--- LaurelBr1.prj (project) ---

Proj Title=LaurelBr1
Current Plan=p01
Default Exp/Contr=0,0
English Units
Geom File=g01
Flow File=f01
Plan File=p01
BEGIN DESCRIPTION:
END DESCRIPTION:
DSS File=dss
DSS Export Rating Curves= 0
DSS Export Rating Curve Sorted= 0
DSS Export Volume Flow Curves= 0
DXF OffsetX= 0
DXF OffsetY= 0
DXF ScaleX= 0
DXF ScaleY= 0

--- LaurelBr1.p01 (plan) ---

Plan Title=Floodplain
Program Version=4.00
Short Identifier=Floodplain
Geom File=g01
Flow File=f01
Subcritical Flow
K Sum by GR= 0
Std Step Tol= 0.01
Critical Tol= 0.01
Num of Std Step Trials= 40
Max Error Tol= 0.3
Flow Tol Ratio= 0.001
Split Flow NTrial= 30
Split Flow Tol= 0.02
Split Flow Ratio= 0.02
Log Output Level= 0
Friction Slope Method= 1
Unsteady Friction Slope Method= 2
Unsteady Bridges Friction Slope Method= 1
Parabolic Critical Depth
Global Vel Dist= 0 , 0 , 0
Global Log Level= 0
CheckData=True
Encroach Param=-1 ,0,0, 0
Run HTab= 0
Run UNet= 0
Run PostProcess= 0
Run WQNet= 0
UNET Theta= 0
UNET Theta Warmup= 0
UNET ZTol= 0
UNET ZSATol= 0
UNET MxIter= 0
UNET MaxInSteps= 0
UNET DtIC= 0
UNET DtMin= 0
UNET MaxCRTS= 0
UNET WFStab= 0
UNET SFStab= 0
UNET WFX= 1
UNET SFX= 1
UNET DSS MLevel= 1
UNET DZMax Abort= 0
UNET Convert EG Bridges= 0
UNET Use Existing IB Tables= 0
UNET Froude Reduction=False
UNET Froude Limit= 0
UNET Froude Power= 0
UNET Time Slicing=0,0, 5
DSS File=dss
Write IC File= 0
Echo Input=False
Echo Output=False
Write Detailed= 0
Detailed Automatic Start=False, 0
WQ ULTIMATE=-1
WQ Max Comp Step=1HOUR
WQ Output Interval=15MIN
WQ Output Selected Increments= 0
WQ Output face flow=0
WQ Output face velocity=0
WQ Output face area=0
WQ Output face dispersion=0
WQ Output cell volume=0
WQ Output cell surface area=0
WQ Output cell continuity=0
WQ Output face conc=0
WQ Output face dconc_dx=0
WQ Output face courant=0
WQ Output face peclet=0
WQ Output face adv mass=0
WQ Output face disp mass=0
WQ Output cell mass=0
WQ Output cell source sink temp=0
WQ Output cell source sink nsm=0
WQ Output MaxMinRange=-1
WQ Daily Max Min Mean=-1
WQ Daily Range=0
WQ Daily Time=0
WQ Create Restart=0
WQ Fixed Restart=0
WQ System Summary=False
Sorting and Armoring Iterations= 10
XS Update Threshold= 0.02
Hydraulics Update Threshold= 0.02
Energy Slope Method= 1
Volume Change Method= 0
XS Weighting Method= 0
Number of US Weighted Cross Sections= 1
Number of DS Weighted Cross Sections= 1
Upstream XS Weight=0.25
Main XS Weight=0.5
Downstream XS Weight=0.25
Number of DS XS's Weighted with US Boundary= 1
Upstream Boundary Weight= 1
Weight of XSs Associated with US Boundary= 0
Number of US XS's Weighted with DS Boundary= 1
Downstream Boundary Weight= 0.5
Weight of XSs Associated with DS Boundary= 0.5
Sediment Output Level= 4
Mass or Volume Output= 0
Output Increment Type= 1
Profile and TS Output Increment= 10
XS Output Flag= 0
XS Output Increment= 10
Disregard all LS=0
Disregard all Conn=0
Disregard all Breaches=0
Disregard all Pumps=0

--- LaurelBr1.f01 (steady flow) ---

Flow Title=NFF Regression Equation
Program Version=4.00
Number of Profiles=1
Profile Names=P100yr
River Rch & RM=LaurelBr1,Main      ,9672.6
614.6777
River Rch & RM=LaurelBr1,Main      ,9405.8
778.8064
River Rch & RM=LaurelBr1,Main      ,9077.7
780.9359
River Rch & RM=LaurelBr1,Main      ,5816
853.8495
River Rch & RM=LaurelBr1,Main      ,4193.2
936.6963
River Rch & RM=LaurelBr1,Main      ,245.5
1015.954
Boundary for River Rch & Prof#=LaurelBr1,Main      ,1
Up Type=0
Dn Type=3
Dn Slope=0.06292

--- LaurelBr1.g01 (geometry) ---

Geom Title=USGS 10m DEM
Program Version=4.00

River Reach=LaurelBr1       ,Main
Reach XY= 30
     1827017.335      242497.661      1826740.67      242478.213
      1826517.56      242577.138     1826418.019      242777.574
     1826151.749      242824.112     1826149.429      242934.115
      1825998.97      243057.129     1825794.977      242998.035
     1825677.754      243042.721     1825249.682      243406.844
     1824975.275      243781.214     1824890.557      243722.792
     1824098.886        244160.6     1824188.216      244563.454
     1824119.211      244715.756     1823747.441      244976.734
     1823648.398      245149.465     1823588.972       245898.23
     1823411.487      246046.398     1823386.924      246159.704
     1823012.146      246309.457     1822959.851      246497.242
     1822695.208      246711.175     1822191.277        246760.3
     1822121.666      247082.228     1821981.137      247296.477
     1821523.844      247375.956     1821037.754      247368.469
     1820904.713      247431.822      1820805.55      247855.597

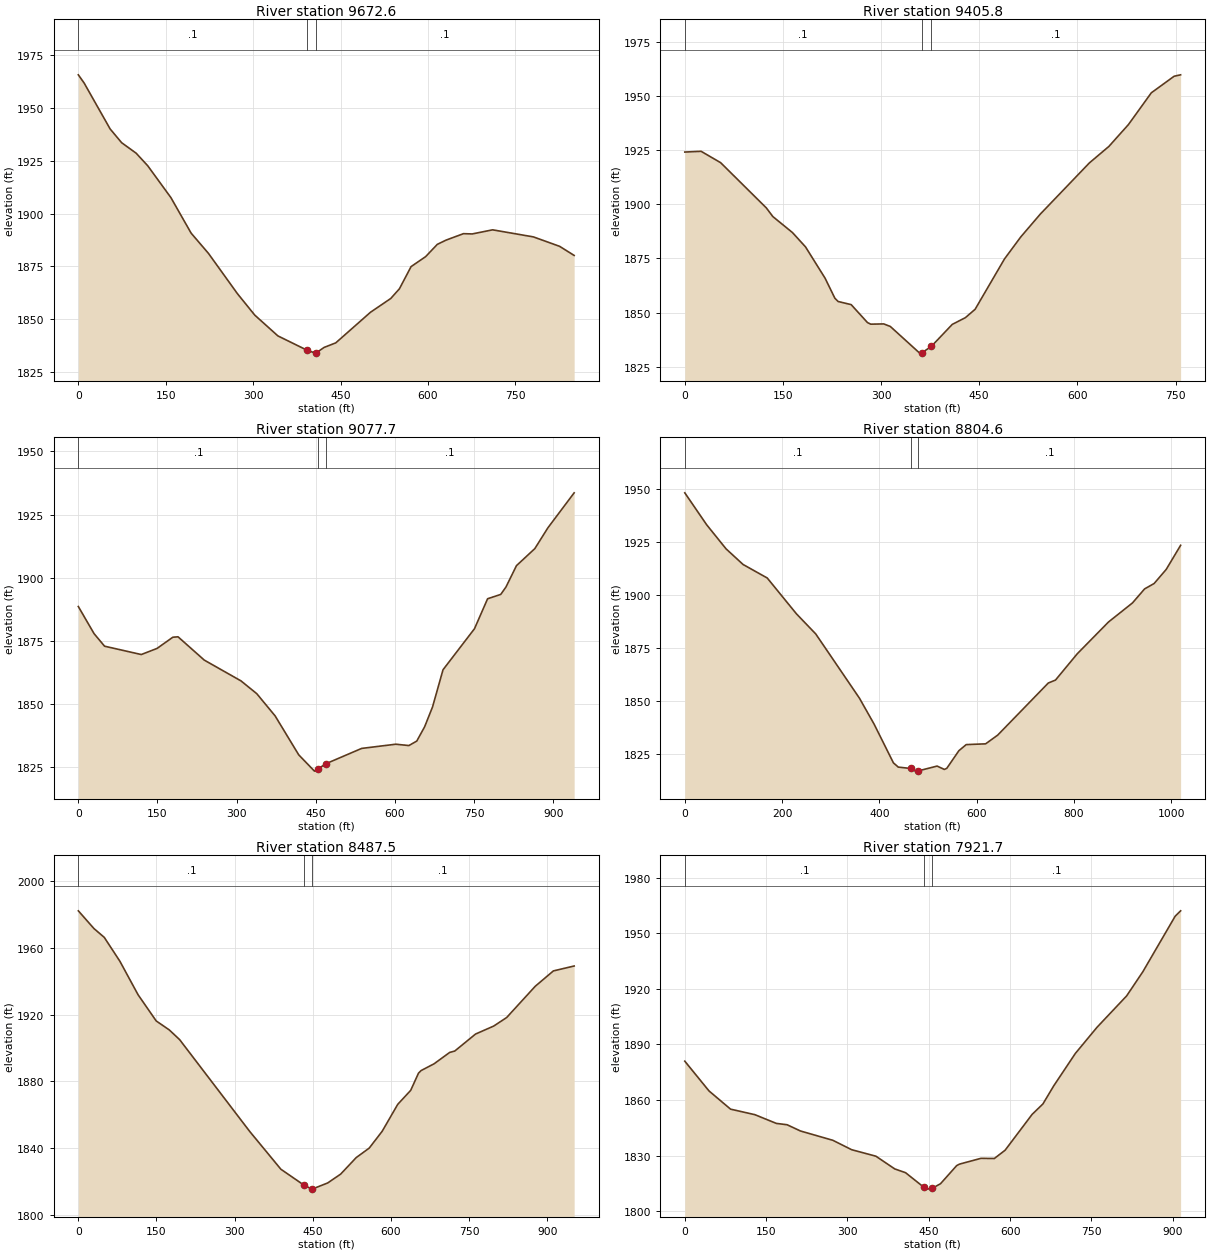
Type RM Length L Ch R = 1 ,9672.6  ,237.3,266.8,272.8
XS GIS Cut Line= 3
     1826337.175      242258.044      1826758.69      242597.024
     1826914.527      242864.802
#Sta/Elev= 30
       0 1965.54     9.9 1961.69    54.6 1939.94    74.4 1933.44    99.2  1928.5
   119.1 1922.55   158.8 1907.52   193.5 1890.73   223.3 1881.14   272.9 1862.13
   302.7 1851.98   342.4 1842.15     393 1835.31   406.9 1834.01     408 1834.11
   421.8 1836.72   441.7 1838.86   501.2 1853.31     536 1859.83   550.9 1864.41
   570.9  1874.9   595.9 1879.62   615.9 1885.41   630.9 1887.42   660.8 1890.47
   675.8 1890.34   710.8 1892.28   780.8 1888.94   825.8 1884.48   850.7 1880.18
#Mann= 3 , 0 , 0
       0      .1       0     393    .045       0     408      .1       0
Bank Sta=393,408
XS Rating Curve= 0 ,0
Exp/Cntr=0.3,0.1

Type RM Length L Ch R = 1 ,9405.8  ,337.4,328,330.5
XS GIS Cut Line= 2
     1826263.484      242373.002       1826746.9      242956.638
#Sta/Elev= 30
       0 1924.09    24.9 1924.44    54.8 1919.18   124.6  1898.3   134.6 1894.29
   164.5 1886.93   184.5  1880.3   214.4 1865.85   229.4 1856.58   234.3 1855.09
   254.3 1853.63   279.2 1845.35   284.2 1844.61   304.1 1844.73   314.1 1843.55
     359 1831.24   361.9 1831.27   376.9 1834.38   408.8 1844.51   428.8 1847.61
   443.7 1851.48   488.6 1874.73   513.5  1884.9   543.4 1895.46   618.2 1919.03
   648.2  1926.7   678.1  1936.8     713 1951.44   747.9  1959.1   757.8 1959.75
#Mann= 3 , 0 , 0
       0      .1       0   361.9    .045       0   376.9      .1       0
Bank Sta=361.9,376.9
XS Rating Curve= 0 ,0
Exp/Cntr=0.3,0.1

Type RM Length L Ch R = 1 ,9077.7  ,277.8,273.1,261.9
XS GIS Cut Line= 3
     1826085.685      242361.351     1826313.594      242944.847
     1826557.572      243141.096
#Sta/Elev= 30
       0 1888.59    29.8 1877.86    49.7 1872.89   119.3 1869.59   149.2 1872.01
     179 1876.43   188.9 1876.61   238.6 1867.39   308.2 1859.16   338.1  1854.1
   372.9  1845.3   417.6  1829.9   447.4 1823.45   454.6  1824.4   469.6 1826.42
   536.9 1832.44   601.6  1834.1   626.4 1833.57   641.3 1835.35   656.2    1841
   671.2 1848.87     691 1863.55   750.7 1879.82   775.5 1891.66   800.4 1893.38
   810.3 1896.31   830.2 1904.76     865 1911.51   889.8 1919.75   939.5 1933.58
#Mann= 3 , 0 , 0
       0      .1       0   454.6    .045       0   469.6      .1       0
Bank Sta=454.6,469.6
XS Rating Curve= 0 ,0
Exp/Cntr=0.3,0.1

Type RM Length L Ch R = 1 ,8804.6  ,304.1,317.1,322.2
XS GIS Cut Line= 3
     1825841.969      242585.233     1826222.217      243104.021
     1826552.354      243283.828
#Sta/Elev= 30
       0 1947.98    44.9 1932.94    84.8 1921.58   119.7 1914.22   169.5 1907.83
   229.4 1890.97   269.2 1881.46     359 1851.19   388.9 1839.05   428.8 1820.72
   438.8 1818.71   464.3 1818.07   473.7 1816.82   479.3  1816.9   518.6  1819.2
   533.5 1817.61   538.5 1818.14   563.4 1826.46   578.4 1829.32   618.3 1829.68
   643.2 1833.81   747.1 1858.34   761.9 1859.73   806.4 1872.06   870.8 1887.09
   920.2  1896.1     945 1902.69   964.7 1905.25   989.5 1911.89  1019.1 1923.25
#Mann= 3 , 0 , 0
       0      .1       0   464.3    .045       0   479.3      .1       0
Bank Sta=464.3,479.3
XS Rating Curve= 0 ,0
Exp/Cntr=0.3,0.1

Type RM Length L Ch R = 1 ,8487.5  ,567.3,565.8,558.2
XS GIS Cut Line= 3
     1825733.335      242594.848     1825906.818      243177.712
     1825991.449      243510.649
#Sta/Elev= 30
       0  1982.3    29.9  1971.7    49.8 1966.38    79.8 1952.07   114.6 1932.03
   149.5 1916.29   174.5 1910.93   194.4 1905.11     329 1850.04   388.8  1827.4
   433.6 1817.77   448.6 1815.48   478.5 1819.16   503.5 1824.47   533.4  1834.4
   558.3 1840.06   583.2 1850.15   613.1 1866.31     638  1874.7   652.9 1884.98
   657.9 1886.54   682.8  1890.6   712.7  1897.4   722.6 1898.27   762.5 1908.45
   797.3 1913.22   822.2 1918.36     877 1937.07   911.8 1946.28   951.7 1949.23
#Mann= 3 , 0 , 0
       0      .1       0   433.6    .045       0   448.6      .1       0
Bank Sta=433.6,448.6
XS Rating Curve= 0 ,0
Exp/Cntr=0.3,0.1

Type RM Length L Ch R = 1 ,7921.7  ,230.1,229.6,230.3
XS GIS Cut Line= 3
      1825148.42      242927.853     1825511.832      243381.101
      1825715.43      243645.421
#Sta/Elev= 30
       0 1880.97    44.7 1864.88    84.4 1855.05   129.1 1852.08   168.8 1847.36
   188.7 1846.62   213.5 1843.24   273.1 1838.22   307.8 1833.14   352.5 1829.63
   387.3 1822.76   407.2 1820.72   441.2  1812.8   446.9 1811.84   456.2 1812.24
   471.7 1814.76   501.5 1824.54   506.5 1825.33   546.2 1828.47     571 1828.39
   590.9 1832.88   640.7 1852.23   660.6 1857.86   680.5 1867.62   720.4 1885.14
   760.2 1899.22     815 1916.23   844.9 1929.28   904.6 1959.32   914.6  1962.2
#Mann= 3 , 0 , 0
       0      .1       0   441.2    .045       0   456.2      .1       0
Bank Sta=441.2,456.2
XS Rating Curve= 0 ,0
Exp/Cntr=0.3,0.1

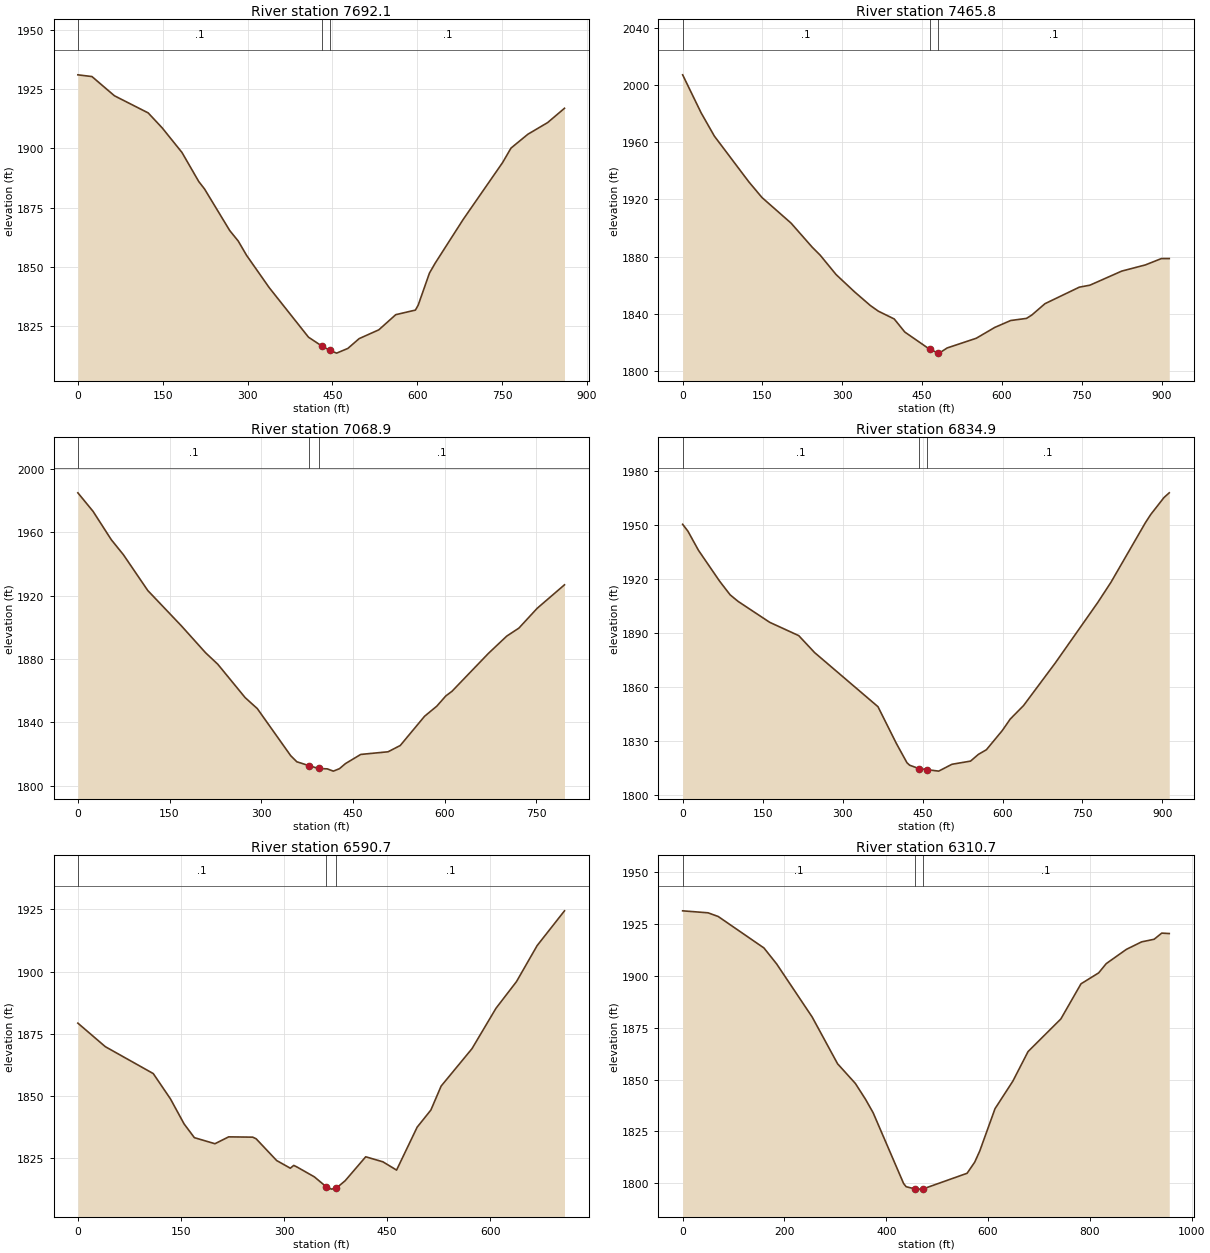
Type RM Length L Ch R = 1 ,7692.1  ,228.3,226.4,217
XS GIS Cut Line= 2
     1824957.673       243080.44     1825529.518      243723.029
#Sta/Elev= 30
       0 1930.97    24.9 1930.24    64.6 1922.15   124.3 1914.92   149.2 1908.57
     184 1898.26   213.8 1885.96   223.8 1882.91   268.5 1865.33   283.4 1860.95
   298.3 1854.87   338.1 1841.33   407.7  1820.4   430.8 1816.76   445.8 1814.81
   457.4 1813.69   477.3 1815.68   497.2  1819.8     532 1823.51   561.9 1829.89
   596.7 1831.83   601.6 1833.92   621.5 1847.42   631.5 1851.56   681.2 1870.06
   750.8    1894   765.7 1900.11   795.6 1905.95   830.4 1910.84   860.2 1916.87
#Mann= 3 , 0 , 0
       0      .1       0   430.8    .045       0   445.8      .1       0
Bank Sta=430.8,445.8
XS Rating Curve= 0 ,0
Exp/Cntr=0.3,0.1

Type RM Length L Ch R = 1 ,7465.8  ,398,396.9,315.6
XS GIS Cut Line= 3
     1824748.197        243274.8     1825100.834      243565.754
     1825475.574       243827.44
#Sta/Elev= 30
       0 2007.39    34.8 1980.68    59.6 1964.42   124.2 1932.42   149.1 1921.33
   203.7  1903.4   243.5 1886.49   258.4 1880.93   288.2 1867.37     323  1855.2
   352.8 1845.58   367.7 1841.66   397.5  1836.2   417.4 1827.02   464.3  1814.9
   479.3 1812.46     482 1812.25   496.9 1815.87   551.6 1822.67   586.3 1830.26
   616.2 1835.11     646 1836.61   655.9 1838.94   680.7 1846.92   745.3 1858.51
   765.2  1859.9   824.8 1869.75   869.5 1874.12   899.3 1878.54   914.2 1878.56
#Mann= 3 , 0 , 0
       0      .1       0   464.3    .045       0   479.3      .1       0
Bank Sta=464.3,479.3
XS Rating Curve= 0 ,0
Exp/Cntr=0.3,0.1

Type RM Length L Ch R = 1 ,7068.9  ,228.1,234,309.2
XS GIS Cut Line= 2
     1824689.436      243392.891     1825102.108        244073.8
#Sta/Elev= 30
       0 1985.07    24.9 1973.34    54.7 1955.44    74.6  1945.9   114.4 1923.33
   169.2 1901.07     209 1883.97   228.9 1876.76   273.7 1855.64   293.6  1848.7
   348.3 1818.91   358.3 1815.09   378.8 1812.57   393.8 1810.86     408 1810.62
     418 1809.19     428 1810.73   437.9 1813.97   462.8 1819.74   507.6 1821.42
   527.5 1825.39   567.3 1843.88   587.2 1850.22   602.1 1856.74   612.1 1859.64
   671.8 1883.62   701.6 1894.48   721.6 1899.58   751.4 1912.05   796.2 1926.94
#Mann= 3 , 0 , 0
       0      .1       0   378.8    .045       0   393.8      .1       0
Bank Sta=378.8,393.8
XS Rating Curve= 0 ,0
Exp/Cntr=0.3,0.1

Type RM Length L Ch R = 1 ,6834.9  ,244.8,244.2,240.9
XS GIS Cut Line= 3
     1824550.745      243398.233     1824702.905      243827.524
     1824864.859      244255.184
#Sta/Elev= 30
       0 1950.37     9.9 1946.55    29.7 1935.94    69.3 1918.85    89.1 1911.25
     104 1907.62   163.4    1896   217.8 1888.63   247.5 1879.24   366.4 1849.23
     401 1828.79   420.8 1818.15   425.8 1816.78   443.2 1814.92   458.2 1814.31
   480.3  1813.5   505.2  1817.3     540 1819.05   554.9 1822.81   569.8 1825.36
   599.6 1836.01   614.5 1842.37   639.4 1849.83     699 1873.48   778.6 1906.98
   803.4  1918.2     868 1951.24     878 1955.79   902.8 1965.19   912.8 1967.82
#Mann= 3 , 0 , 0
       0      .1       0   443.2    .045       0   458.2      .1       0
Bank Sta=443.2,458.2
XS Rating Curve= 0 ,0
Exp/Cntr=0.3,0.1

Type RM Length L Ch R = 1 ,6590.7  ,275.1,279.9,278.9
XS GIS Cut Line= 2
     1824365.194      243619.861     1824668.802      244259.502
#Sta/Elev= 30
       0 1879.27    39.9 1869.81   109.7 1858.98   134.6 1848.84   154.6 1838.71
   169.5  1833.2   199.4 1830.76   219.4 1833.52   254.3  1833.4   259.3 1832.76
   289.2    1824   309.1 1820.91   314.1 1822.04   319.1 1821.35     344 1817.44
     361 1813.52     369 1812.49     376 1812.88   388.9 1815.87   418.8  1825.5
   443.8 1823.48   463.7 1820.15   493.6  1837.4   513.6 1844.31   528.5 1853.94
   573.4 1868.99   608.3 1885.24   638.2    1896   668.2 1910.47     708 1924.46
#Mann= 3 , 0 , 0
       0      .1       0     361    .045       0     376      .1       0
Bank Sta=361,376
XS Rating Curve= 0 ,0
Exp/Cntr=0.3,0.1

Type RM Length L Ch R = 1 ,6310.7  ,84.8,85.2,85.2
XS GIS Cut Line= 3
     1824083.939      243663.071     1824418.252      244253.607
     1824662.261      244385.667
#Sta/Elev= 30
       0 1931.49    49.9 1930.53    69.9 1928.75   159.7 1913.57   184.6 1905.89
   254.5 1880.23   304.4 1857.67   339.3  1848.2   359.3 1840.53   374.2 1834.07
   434.1  1799.9   439.1 1798.35   457.4 1797.24     464 1797.19   472.4  1797.3
   558.8 1804.84   573.8 1810.22   583.8 1815.66   613.7 1836.02   648.7  1849.3
   678.6 1863.57     743 1879.31   782.6 1896.27   817.3 1901.54   832.2 1906.02
   871.8  1912.9   901.6  1916.5   926.3 1917.77   941.2 1920.73     956 1920.53
#Mann= 3 , 0 , 0
       0      .1       0   457.4    .045       0   472.4      .1       0
Bank Sta=457.4,472.4
XS Rating Curve= 0 ,0
Exp/Cntr=0.3,0.1

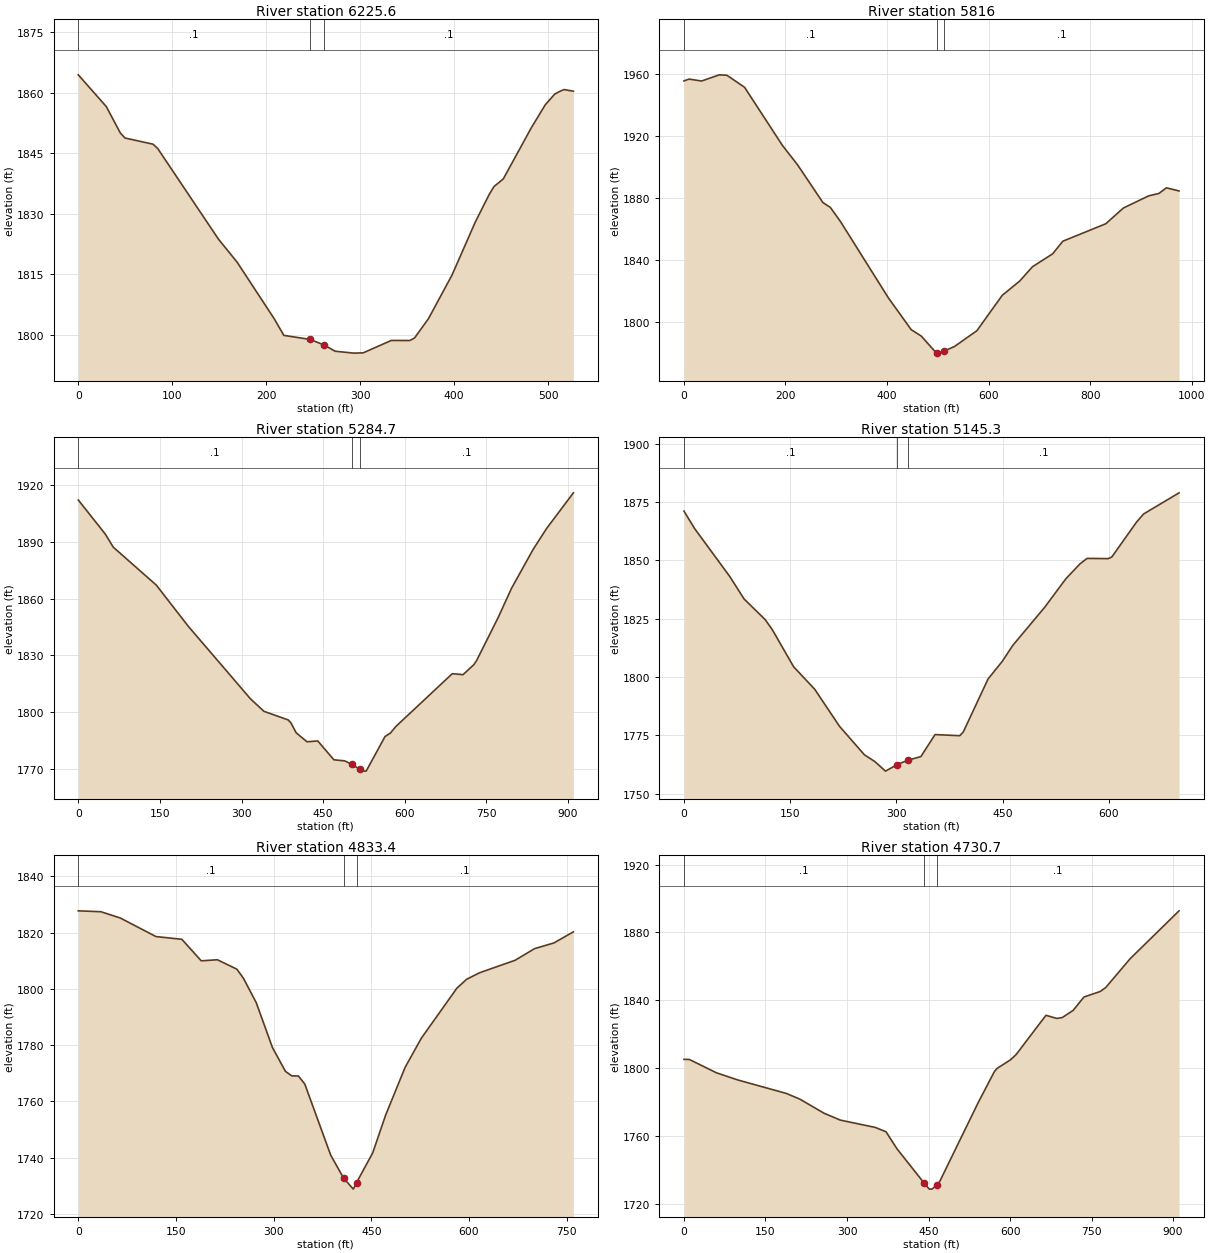
Type RM Length L Ch R = 1 ,6225.6  ,431,409.5,383.7
XS GIS Cut Line= 2
     1824108.605      243884.453      1824377.91      244337.196
#Sta/Elev= 30
       0 1864.39    29.8 1856.52    44.7 1849.99    49.7 1848.73    79.5  1847.2
    84.5 1846.13   149.1 1823.67     169 1817.95   208.7 1803.84   218.7  1799.8
   246.6  1798.8   261.6 1797.41   273.3 1795.87   293.2  1795.4   303.2 1795.47
     333 1798.54   352.8 1798.53   357.8 1799.16   372.7 1803.98   397.6 1814.73
   422.4 1827.88   437.3 1834.77   442.3 1836.69   452.2 1838.58   482.1 1851.29
     497    1857   506.9  1859.6   511.9 1860.24   516.8 1860.74   526.8 1860.33
#Mann= 3 , 0 , 0
       0      .1       0   246.6    .045       0   261.6      .1       0
Bank Sta=246.6,261.6
XS Rating Curve= 0 ,0
Exp/Cntr=0.3,0.1

Type RM Length L Ch R = 1 ,5816    ,516.1,531.3,546.3
XS GIS Cut Line= 3
     1823653.952      244393.875     1824285.607      244383.304
     1824616.981      244473.795
#Sta/Elev= 30
       0 1955.24      10 1956.42    34.8 1955.18    69.6 1959.16    84.6 1958.88
   119.4 1951.15     194 1913.78   223.8 1901.31   273.6 1877.11   288.5 1873.89
   308.4 1864.82   402.9 1815.69   447.7 1795.36   467.6 1791.21   497.4 1780.29
   498.2  1780.3   513.2 1781.78   532.3 1784.43     577 1794.69   626.8 1817.39
   661.6  1826.7   686.5 1835.82   726.3 1844.13   746.2  1852.2   830.9 1863.44
   865.7 1873.58   915.5 1881.39   935.4 1882.91   950.4 1886.53   975.2 1884.54
#Mann= 3 , 0 , 0
       0      .1       0   498.2    .045       0   513.2      .1       0
Bank Sta=498.2,513.2
XS Rating Curve= 0 ,0
Exp/Cntr=0.3,0.1

Type RM Length L Ch R = 1 ,5284.7  ,140.7,139.4,138.2
XS GIS Cut Line= 3
     1823593.205      244525.475     1823951.316      244806.156
     1824309.426      245086.837
#Sta/Elev= 30
       0 1912.09    49.5 1894.12    64.3 1887.16   143.4 1867.11   202.8 1845.13
   316.5    1807   341.2 1800.41   385.8 1795.86   390.7 1794.35   400.6 1789.02
   420.4 1784.32   440.2 1784.74   469.8  1774.8   489.6 1774.22   502.4 1772.48
   517.4 1769.75   524.2  1768.8   529.2 1768.85   563.8 1787.09   573.7 1788.92
   583.6 1792.37   687.4  1820.3   707.2 1819.79     727 1825.07     732 1827.18
   771.5 1849.83   796.2 1865.36   835.8 1885.87   860.5 1896.92     910 1915.88
#Mann= 3 , 0 , 0
       0      .1       0   502.4    .045       0   517.4      .1       0
Bank Sta=502.4,517.4
XS Rating Curve= 0 ,0
Exp/Cntr=0.3,0.1

Type RM Length L Ch R = 1 ,5145.3  ,321.3,311.9,311.1
XS GIS Cut Line= 2
     1823631.227      244731.127     1824200.125      245137.903
#Sta/Elev= 30
       0 1871.16      15 1863.71    64.9 1843.04    84.9  1833.5   114.9 1824.57
   124.9 1820.26   154.9 1804.42   184.8 1794.73   219.8 1778.85   254.8 1766.69
   269.8 1763.71   284.7 1759.64     301 1762.41     316 1764.29   334.7 1765.88
   354.7 1775.31   389.6 1774.84   394.6 1776.44   429.6 1799.15   449.6 1806.69
   464.6 1813.59   509.5 1829.88   539.5 1842.13   559.5 1848.55   569.5 1850.88
   599.5 1850.78   604.4 1851.48   639.4 1866.46   649.4 1869.94   699.4    1879
#Mann= 3 , 0 , 0
       0      .1       0     301    .045       0     316      .1       0
Bank Sta=301,316
XS Rating Curve= 0 ,0
Exp/Cntr=0.3,0.1

Type RM Length L Ch R = 1 ,4833.4  ,101.3,102.6,104.2
XS GIS Cut Line= 2
     1823407.206      244987.573     1824102.852      245294.129
#Sta/Elev= 30
       0 1827.73    34.8 1827.41    64.6 1825.17   119.2 1818.59     159 1817.61
   188.8 1809.96   213.6 1810.35   243.5 1806.99   253.4 1803.84   273.3 1795.07
   298.1 1779.16     318 1770.71   327.9 1769.07   337.9 1769.06   347.8 1766.18
   387.6  1740.9   407.4 1732.74   422.3 1728.84   427.3 1731.17   452.1 1741.74
     472  1755.2   501.8 1772.09   526.7 1782.46   581.3 1800.24   596.2 1803.39
   616.1 1805.72   670.8 1810.17   700.6 1814.29   730.4 1816.33   760.2 1820.26
#Mann= 3 , 0 , 0
       0      .1       0   407.4    .045       0   427.3      .1       0
Bank Sta=407.4,427.3
XS Rating Curve= 0 ,0
Exp/Cntr=0.3,0.1

Type RM Length L Ch R = 1 ,4730.7  ,545.2,537.6,529.7
XS GIS Cut Line= 3
     1823348.787      245052.871     1823756.104      245258.185
     1824154.114      245478.115
#Sta/Elev= 30
       0 1805.21     9.9 1805.16    59.5 1797.33    99.2 1793.06   188.4 1785.13
   213.2 1781.78   257.8 1773.46   287.6 1769.42     352  1765.1   371.8 1762.54
   391.7 1752.62   441.3 1732.53   451.2 1728.77   456.1 1728.73   466.1  1731.2
   471.1 1733.57   541.1 1779.56   571.1 1797.97   576.1 1799.88     601 1804.99
     611 1807.98     666 1831.18     686 1829.35     696 1829.85     716 1834.07
     736 1841.96     766 1845.24     776 1847.56   820.9 1864.52   910.9 1892.76
#Mann= 3 , 0 , 0
       0      .1       0   441.3    .045       0   466.1      .1       0
Bank Sta=441.3,466.1
XS Rating Curve= 0 ,0
Exp/Cntr=0.3,0.1

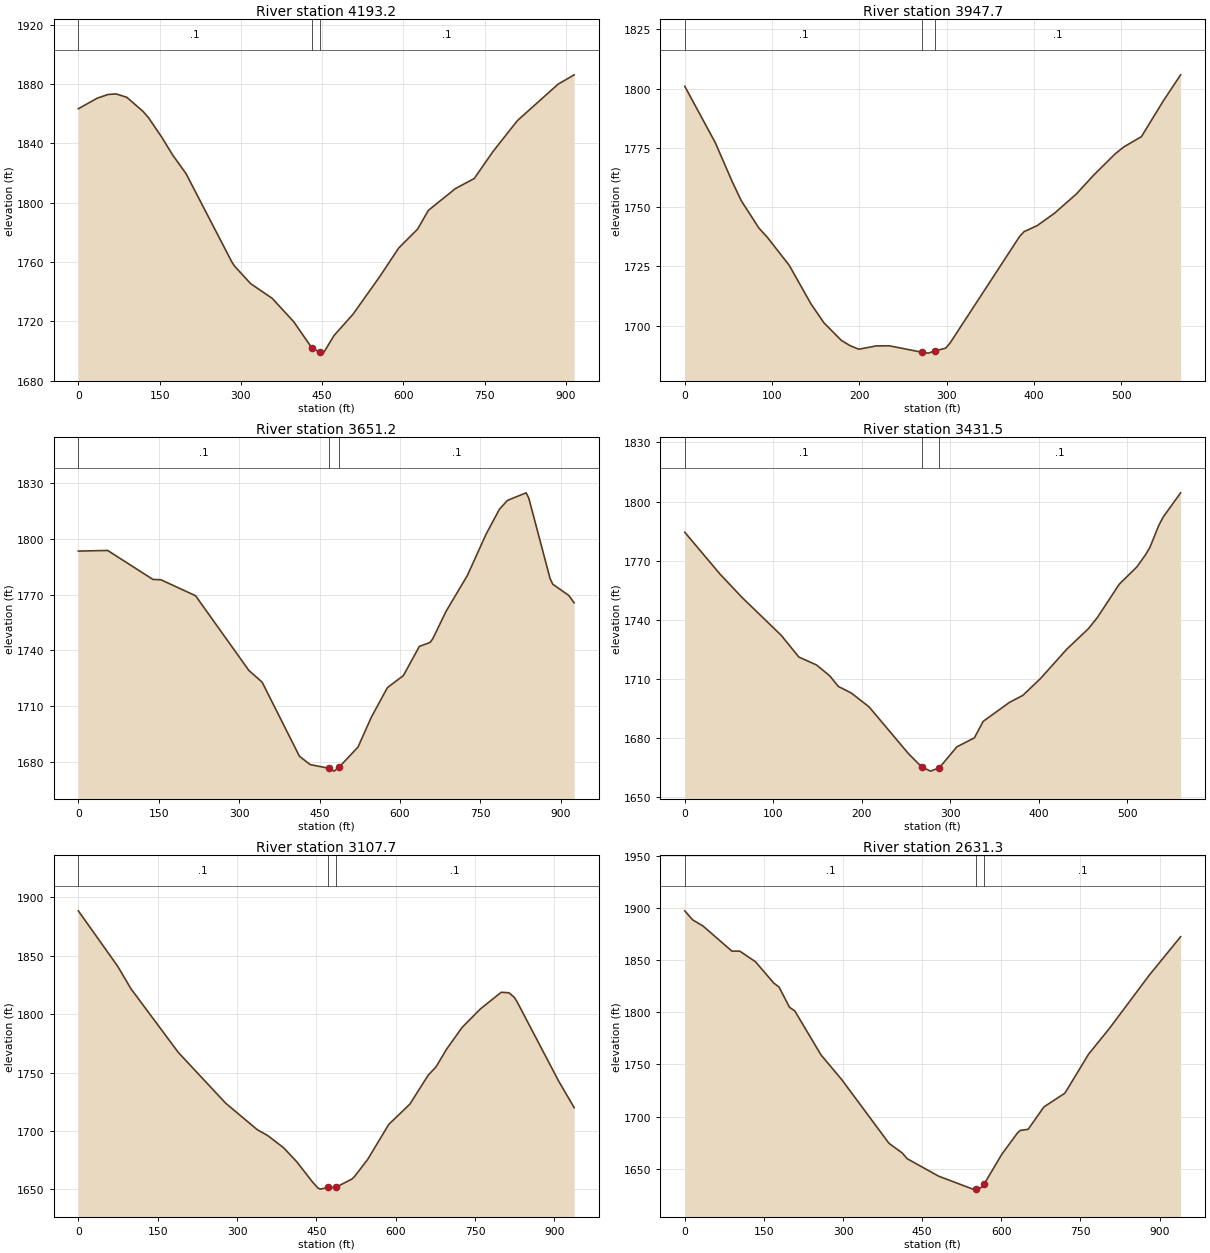
Type RM Length L Ch R = 1 ,4193.2  ,235.1,245.5,255.9
XS GIS Cut Line= 3
     1823141.606      245636.147     1823775.663      245730.382
      1824049.72      245725.796
#Sta/Elev= 30
       0  1863.3    34.8 1870.41    54.7 1872.92    69.6 1873.31    89.4 1871.04
   119.3 1861.57   129.2 1857.44     154 1844.15   173.9 1832.24   198.8 1819.57
   283.2 1760.12   288.2  1757.3     318 1745.43   357.8 1735.52   397.5 1719.78
   431.2 1701.99   446.2  1699.2   452.2 1698.59   472.1 1710.54   506.8 1724.73
   556.6 1750.34   591.3 1769.44   626.1 1782.14     646  1794.8   695.8 1809.46
   730.7 1816.29   765.6 1834.63   810.5 1855.37   885.2  1879.8   915.1 1886.17
#Mann= 3 , 0 , 0
       0      .1       0   431.2    .045       0   446.2      .1       0
Bank Sta=431.2,446.2
XS Rating Curve= 0 ,0
Exp/Cntr=0.3,0.1

Type RM Length L Ch R = 1 ,3947.7  ,289.6,296.5,303.1
XS GIS Cut Line= 2
     1823330.567       245783.44     1823805.139      246095.891
#Sta/Elev= 30
       0 1800.94    34.9 1777.21    54.8 1760.37    64.8 1752.66    84.7  1741.3
    94.7 1737.23   119.6 1725.52   144.5 1709.28   159.5 1701.21   179.4 1693.83
   189.4 1691.61   199.4  1690.1   219.3 1691.49   234.3 1691.54   271.6 1688.84
   279.1 1688.45   286.6 1689.37     299 1690.56     304 1692.72   383.8  1737.7
   388.8 1739.67   403.7 1742.18   423.6  1747.4   448.6 1755.51   468.5 1763.46
   493.4 1772.54   503.4 1775.46   523.3 1779.72   548.3 1794.76   568.2 1805.78
#Mann= 3 , 0 , 0
       0      .1       0   271.6    .045       0   286.6      .1       0
Bank Sta=271.6,286.6
XS Rating Curve= 0 ,0
Exp/Cntr=0.3,0.1

Type RM Length L Ch R = 1 ,3651.2  ,214.9,219.7,224.8
XS GIS Cut Line= 3
     1823067.558      245760.886     1823492.688      246266.855
      1823722.84      246395.832
#Sta/Elev= 30
       0 1793.51    54.7 1793.85   139.1 1778.24     154 1778.06   218.6 1769.46
     318 1729.21   342.8 1722.87   412.4 1682.92   432.3 1678.46   467.1 1676.47
     477 1674.92     487 1677.24   521.7 1687.95   546.6 1704.08   576.4 1719.91
   606.2 1726.42     636 1742.15   655.9 1744.26   660.9  1746.2   685.8 1761.04
   725.6 1780.39   760.4 1802.61   785.3 1816.03   800.2 1820.81   835.1 1824.91
   840.1 1822.05   879.9  1778.6   884.9 1775.64   914.7  1769.6   924.7 1765.62
#Mann= 3 , 0 , 0
       0      .1       0   467.1    .045       0     487      .1       0
Bank Sta=467.1,487
XS Rating Curve= 0 ,0
Exp/Cntr=0.3,0.1

Type RM Length L Ch R = 1 ,3431.5  ,329.5,323.8,326.2
XS GIS Cut Line= 2
     1823059.382      245975.037     1823321.724      246470.244
#Sta/Elev= 30
       0 1784.41    39.7 1763.26    64.5 1751.44   109.1  1732.1   128.9 1721.12
   148.8 1717.13   163.7 1711.64   173.6  1706.2   188.4  1702.8   208.3 1695.83
   252.9 1672.06   267.8 1665.37   277.7 1663.25   287.6  1664.9   307.5 1675.58
   327.3 1680.12   337.2 1688.48     367 1698.14   381.9 1701.63   401.7 1710.07
   431.5    1725   456.3 1735.57   466.2 1741.11     491 1758.04   510.8 1766.77
   520.7 1772.97   525.7 1776.76   535.6 1787.76   540.6 1792.09   560.4 1804.42
#Mann= 3 , 0 , 0
       0      .1       0   267.8    .045       0   287.6      .1       0
Bank Sta=267.8,287.6
XS Rating Curve= 0 ,0
Exp/Cntr=0.3,0.1

Type RM Length L Ch R = 1 ,3107.7  ,464.5,476.5,491.8
XS GIS Cut Line= 3
     1822593.266      246144.622     1823147.812      246514.458
     1823326.414      246718.143
#Sta/Elev= 30
       0 1888.49    74.6 1840.93    99.5  1821.8     189 1767.34   278.6 1723.85
   338.2 1701.23   358.2 1696.11     388 1685.78   412.9 1673.79   442.7 1656.47
   452.7  1651.4   457.6 1650.31   471.9 1651.72   486.9 1651.86   517.3 1658.95
   522.3 1661.14   547.2  1675.8     587 1705.74   626.8 1723.02   661.6 1747.88
   676.4 1754.97   696.1 1769.97   725.7 1788.76   760.1 1804.48   799.6 1818.79
   814.3 1818.34   824.2 1814.51   829.1 1811.07   907.9 1743.02   937.5 1720.07
#Mann= 3 , 0 , 0
       0      .1       0   471.9    .045       0   486.9      .1       0
Bank Sta=471.9,486.9
XS Rating Curve= 0 ,0
Exp/Cntr=0.3,0.1

Type RM Length L Ch R = 1 ,2631.3  ,206.4,202.4,198.4
XS GIS Cut Line= 3
     1822465.771      246189.633     1822645.993      246646.753
     1822723.025      247088.672
#Sta/Elev= 30
       0 1897.32    14.9 1888.66    34.7 1882.69    89.3 1858.67   104.2 1858.67
     134 1848.52   168.8 1827.99   178.7 1824.24   198.5 1804.82   208.5 1801.39
   258.1 1759.26   297.8 1735.29   387.1 1674.38     412  1665.2   421.9 1659.52
   481.4 1642.83   546.2 1630.44   552.1 1630.63   561.1 1631.63   567.1 1634.93
     601 1663.87   630.9 1684.45   635.9 1686.72   650.9  1687.8   680.8 1709.27
   720.6 1722.43   765.5 1759.86   805.4  1784.8   880.1 1835.33     940  1872.5
#Mann= 3 , 0 , 0
       0      .1       0   552.1    .045       0   567.1      .1       0
Bank Sta=552.1,567.1
XS Rating Curve= 0 ,0
Exp/Cntr=0.3,0.1

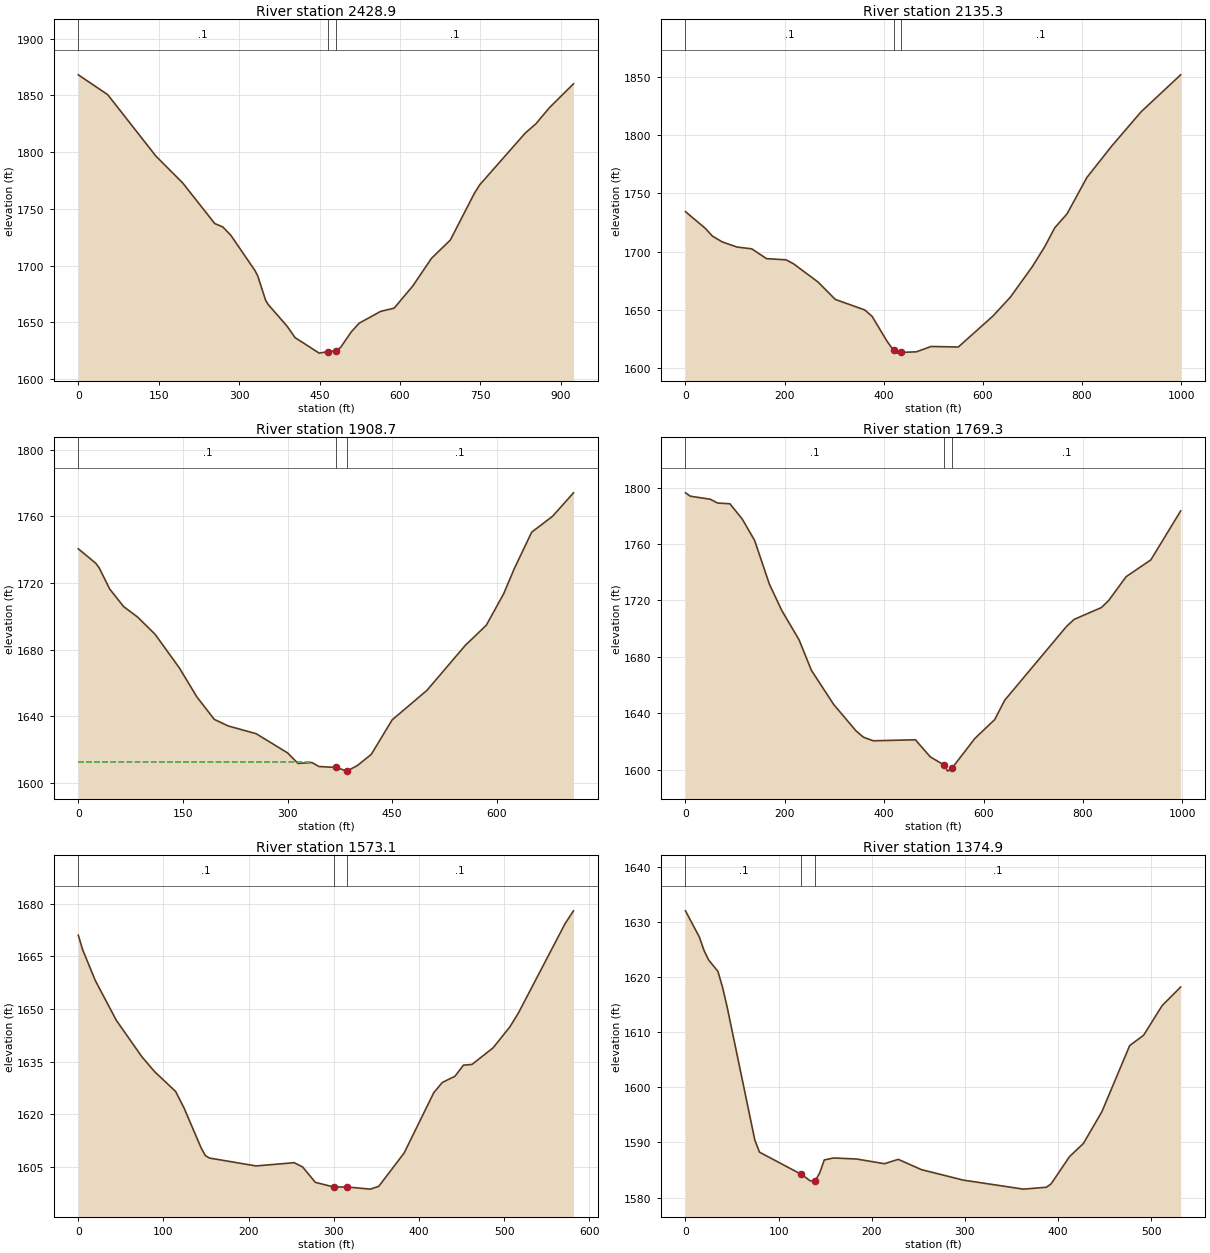
Type RM Length L Ch R = 1 ,2428.9  ,303,293.6,284
XS GIS Cut Line= 2
      1822307.73      246266.855     1822602.496      247142.309
#Sta/Elev= 30
       0 1868.12    54.9 1850.66   144.8 1796.51   194.7 1772.92   254.6 1737.08
   269.6 1734.11   284.6 1726.74   329.6  1695.7   334.6 1691.16   349.5 1669.49
   354.5 1665.63   389.5 1646.71   404.4  1636.6   449.4 1622.94   465.5 1624.23
   480.5 1625.01   489.3 1627.93   509.3 1641.71   524.3 1649.42   564.2 1659.75
   589.2 1662.55   624.2 1682.23   659.1 1706.57   694.1 1722.61     739 1763.82
     749 1771.31   833.9 1816.84   853.8 1825.04   878.8 1839.12   923.8  1860.2
#Mann= 3 , 0 , 0
       0      .1       0   465.5    .045       0   480.5      .1       0
Bank Sta=465.5,480.5
XS Rating Curve= 0 ,0
Exp/Cntr=0.3,0.1

Type RM Length L Ch R = 1 ,2135.3  ,228.6,226.6,224.7
XS GIS Cut Line= 3
     1821887.419      246460.438     1822183.093      246780.754
     1822568.145      247191.664
#Sta/Elev= 30
       0 1734.27    39.6 1720.11    54.5  1713.2    74.3 1708.26     104 1703.86
   133.8 1702.32   163.5 1693.92   203.1 1692.86     218 1689.48   267.5 1673.79
   302.2 1658.86   361.6 1649.83   376.5  1644.3   406.2 1623.22   419.7  1615.1
     426  1612.7   434.7  1613.3   465.8 1613.83   495.7 1618.42   550.5 1617.98
   620.3 1644.59   655.2 1660.65     700 1687.19     725 1704.31   744.9 1720.36
   769.8 1732.39   809.7 1763.55   859.5 1790.44   919.3 1820.16     999 1851.86
#Mann= 3 , 0 , 0
       0      .1       0   419.7    .045       0   434.7      .1       0
Bank Sta=419.7,434.7
XS Rating Curve= 0 ,0
Exp/Cntr=0.3,0.1

Type RM Length L Ch R = 1 ,1908.7  ,136.2,139.4,142.6
XS GIS Cut Line= 2
     1821856.739      246753.219     1822405.003       247204.21
#Sta/Elev= 30
       0 1740.61      25 1731.96      30 1729.13      45 1716.47      65  1705.9
      85 1699.62     110 1689.33     145 1669.04     170 1651.69     195  1638.2
     215 1634.24     255 1629.61     300  1618.1     315 1611.76     335 1612.29
     345 1609.91   370.1 1609.34     385 1607.14   385.1 1607.17     400 1610.46
     420 1617.19     450 1637.94   499.9 1655.66   554.9 1682.68   584.9  1694.7
   609.9 1713.68   624.9 1728.57   649.9 1750.54   679.9 1760.12   709.9  1774.2
#Mann= 3 , 0 , 0
       0      .1       0   370.1    .045       0   385.1      .1       0
#XS Ineff= 2 , 0
          334.46 1612.35
Permanent Ineff=
       F       F
Bank Sta=370.1,385.1
XS Rating Curve= 0 ,0
Exp/Cntr=0.3,0.1

Type RM Length L Ch R = 1 ,1769.3  ,191.6,196.2,200.9
XS GIS Cut Line= 3
     1821661.406      246857.578     1821977.593       246977.24
     1822401.636        247481.3
#Sta/Elev= 30
       0 1796.29     9.9 1793.89    49.7 1791.78    64.6 1789.07    89.5 1788.54
   114.4 1777.65   139.2 1762.56     169 1731.52   193.9 1712.91   228.7 1692.12
   253.6 1670.47   298.3 1646.38   343.1  1627.7     358 1623.19     378  1620.6
   462.8 1621.32   492.8  1609.2   521.2 1603.33   527.7  1599.1   536.2 1601.06
   582.6 1622.28   622.5 1635.63   642.5 1649.28   767.2  1701.7   782.2 1706.58
   837.1 1714.97   852.1 1720.06     887 1736.86   936.9 1748.82   996.8 1783.46
#Mann= 3 , 0 , 0
       0      .1       0   521.2    .045       0   536.2      .1       0
Bank Sta=521.2,536.2
XS Rating Curve= 0 ,0
Exp/Cntr=0.3,0.1

Type RM Length L Ch R = 1 ,1573.1  ,188.5,198.1,207.8
XS GIS Cut Line= 2
     1821850.843      247012.612      1822119.08      247528.452
#Sta/Elev= 30
       0 1671.08       5 1667.02    19.9 1658.18    44.7 1646.79    74.5 1636.47
    89.4 1632.22   114.3 1626.52   124.2 1621.79   144.1  1610.5   149.1 1608.27
     154 1607.54   208.7 1605.29   253.4 1606.22   263.4 1604.99   278.3 1600.61
   300.3 1599.27   315.3  1599.3   342.9 1598.68   352.8 1599.48   382.6    1609
   417.4 1626.18   427.4 1629.09   442.3 1630.87   452.2 1634.03   462.2 1634.22
     487 1638.96   506.9 1644.99   516.8 1648.92   571.5 1674.35   581.4 1678.02
#Mann= 3 , 0 , 0
       0      .1       0   300.3    .045       0   315.3      .1       0
Bank Sta=300.3,315.3
XS Rating Curve= 0 ,0
Exp/Cntr=0.3,0.1

Type RM Length L Ch R = 1 ,1374.9  ,165.6,168.4,171.1
XS GIS Cut Line= 2
     1821793.474      247184.762     1821825.898       247715.34
#Sta/Elev= 30
       0 1632.01    14.9 1627.26    19.9 1624.84    24.8 1623.12    34.8 1621.04
    39.7 1618.22    44.7 1614.61    74.5 1590.41    79.5 1588.24   124.5 1584.21
   134.1 1583.03   139.5  1583.1   144.1 1584.48     149 1586.83     159 1587.19
   183.8    1587   213.6 1586.15   228.5 1586.94   253.4 1585.07   298.1 1583.18
   362.7 1581.54   387.5 1581.88   392.5 1582.49   412.3 1587.44   427.2 1589.82
   447.1  1595.6   476.9 1607.58   491.8 1609.44   511.7 1614.82   531.6 1618.19
#Mann= 3 , 0 , 0
       0      .1       0   124.5    .045       0   139.5      .1       0
#XS Ineff= 2 , 0
                          163.59         1587.11
Permanent Ineff=
       F       F
Bank Sta=124.5,139.5
XS Rating Curve= 0 ,0
Exp/Cntr=0.3,0.1