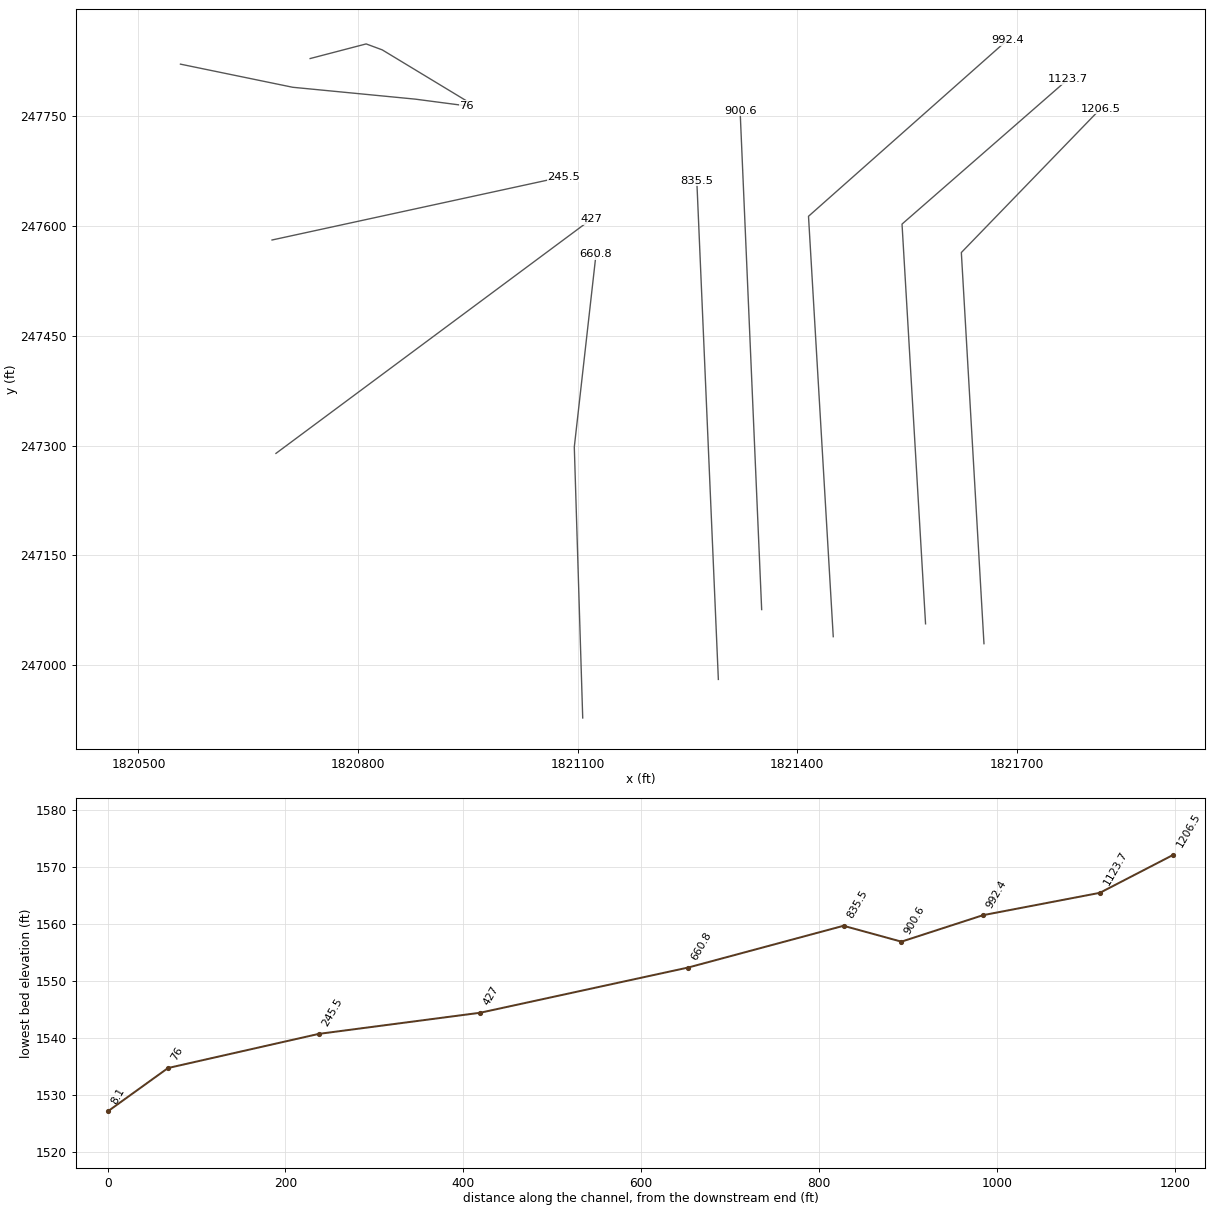
HEC-RAS study LaurelBr1.prj: LaurelBr1

--- LaurelBr1.g01 (geometry) --- (continued)

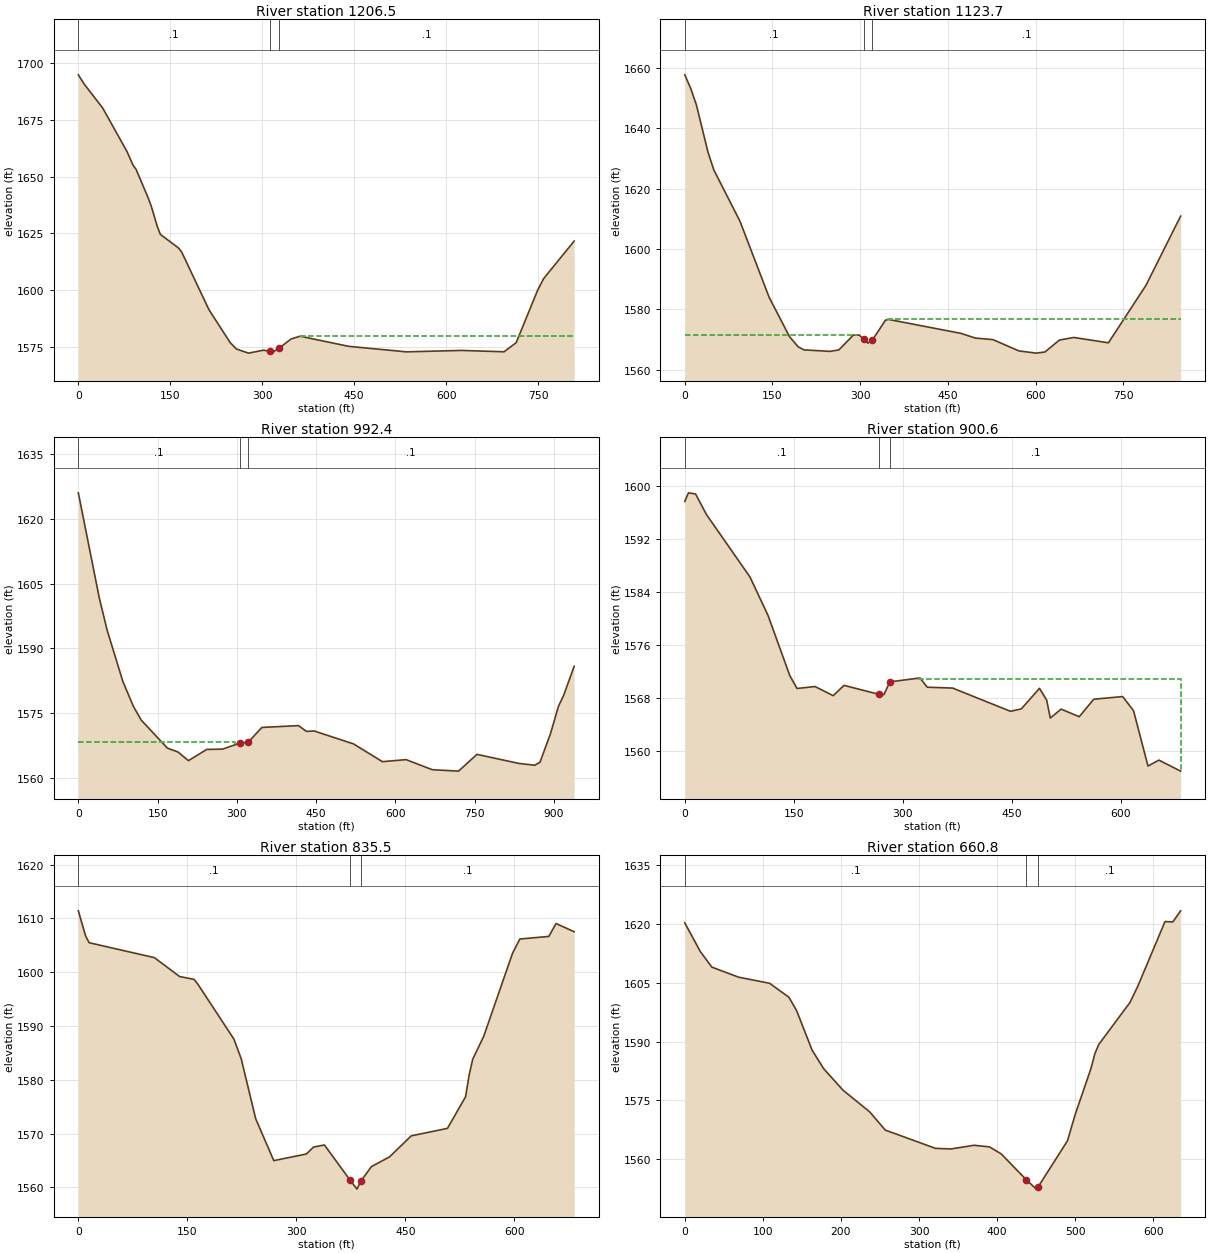
Type RM Length L Ch R = 1 ,1206.5  ,82.8,82.8,83
XS GIS Cut Line= 3
     1821655.068      247029.492     1821624.151       247563.83
     1821814.415      247760.415
#Sta/Elev= 30
       0 1694.91     9.9  1690.7    39.6 1680.32    79.3 1661.12    89.2 1655.04
    94.2 1653.21     114 1640.56   118.9    1637   128.8    1628   133.8 1624.52
   163.5 1618.48   168.5 1616.76   213.1 1591.26   247.8 1576.72   257.7 1573.93
   277.5 1572.11   302.3 1573.42     312 1572.91   317.2 1572.52     327 1574.17
   346.9 1578.35   361.8 1579.58   441.1  1575.1   535.2 1572.67   624.8  1573.3
   694.4  1572.7   714.3 1576.75   749.1  1599.8   759.1 1605.02   808.8 1621.56
#Mann= 3 , 0 , 0
       0      .1       0     312    .045       0     327      .1       0
#XS Ineff= 2 , 0
                          361.38         1579.58
Permanent Ineff=
       F       F
Bank Sta=312,327
XS Rating Curve= 0 ,0
Exp/Cntr=0.3,0.1

Type RM Length L Ch R = 1 ,1123.7  ,132,131.3,130.6
XS GIS Cut Line= 3
     1821575.262      247056.626     1821543.118      247602.699
     1821769.993      247800.709
#Sta/Elev= 30
       0 1657.81      10 1653.37    19.9 1647.79    39.8 1632.06    49.7 1626.23
    94.5 1609.17   144.2 1584.01     179 1570.95   193.9 1567.54   203.9 1566.52
   248.6 1566.02   263.6 1566.51   288.4 1571.44   298.4 1571.44   305.7 1570.09
   313.3 1568.76   320.7  1569.7   343.1 1576.33   348.1 1576.64   472.4    1572
   497.3 1570.42   527.1 1569.93   571.7 1566.17   601.3 1565.44   616.1 1565.82
   640.8 1569.77   665.5 1570.64   724.7 1568.87   788.9 1587.94   848.2 1610.91
#Mann= 3 , 0 , 0
       0      .1       0   305.7    .045       0   320.7      .1       0
#XS Ineff= 2 , 0
          294.95 1571.48  347.21         1576.75
Permanent Ineff=
       F       F
Bank Sta=305.7,320.7
XS Rating Curve= 0 ,0
Exp/Cntr=0.3,0.1

Type RM Length L Ch R = 1 ,992.4   ,91.9,91.8,91.7
XS GIS Cut Line= 3
     1821449.168      247039.069     1821415.362      247613.362
     1821686.875      247853.989
#Sta/Elev= 30
       0 1626.05    39.7 1601.66    54.6 1594.16    84.3  1582.3   104.2 1576.54
     119 1573.35   168.6 1566.86   188.5 1565.97   208.3 1563.96     243 1566.56
   272.8 1566.63   306.1 1568.04   321.1 1568.17   347.2 1571.66   416.6 1572.08
   431.5 1570.75   446.3 1570.83   520.7 1567.84   575.3 1563.72     620  1564.2
   669.7 1561.86   719.4 1561.53   754.2 1565.42   833.7 1563.31   863.5  1562.9
   873.5  1563.6   893.4 1570.24   908.3 1576.53   918.2 1579.09   938.1 1585.83
#Mann= 3 , 0 , 0
       0      .1       0   306.1    .045       0   321.1      .1       0
#XS Ineff= 2 , 0
          296.72 1568.31   391.5         1571.91
Permanent Ineff=
       F       F
Bank Sta=306.1,321.1
XS Rating Curve= 0 ,0
Exp/Cntr=0.3,0.1

Type RM Length L Ch R = 1 ,900.6   ,65,65.1,65.3
XS GIS Cut Line= 2
     1821351.371      247076.111     1821321.926      247757.632
#Sta/Elev= 30
       0 1597.74       5 1599.04    14.9 1598.86    29.9 1595.73    89.6 1586.31
   114.5 1580.48   144.4 1571.38   154.4 1569.41   179.2  1569.7   204.2 1568.32
   219.1 1569.88   267.2 1568.52   273.9 1568.47   282.2 1570.41   323.6    1571
   333.6  1569.6   368.5 1569.47   448.1 1565.95   463.1 1566.32     488 1569.43
   497.9 1567.65   502.9 1564.93   517.8 1566.28   542.7 1565.13   562.7 1567.78
   602.5 1568.18   617.4 1566.05   637.3 1557.66   652.3 1558.56   682.2 1556.89
#Mann= 3 , 0 , 0
       0      .1       0   267.2    .045       0   282.2      .1       0
#XS Ineff= 2 , 0
                          320.55         1570.91
Permanent Ineff=
       F       F
Bank Sta=267.2,282.2
XS Rating Curve= 0 ,0
Exp/Cntr=0.3,0.1

Type RM Length L Ch R = 1 ,835.5   ,190.5,174.7,182.4
XS GIS Cut Line= 2
     1821292.208      246980.658     1821262.763      247662.179
#Sta/Elev= 30
       0 1611.42      10 1606.75    14.9 1605.49   104.6 1602.72   139.4  1599.2
   159.3 1598.67   164.3 1597.81   214.1 1587.56   224.1 1583.92     244 1572.77
   268.9 1564.97   313.7  1566.2   323.6 1567.49   338.6 1567.88   373.7 1561.38
   383.4 1559.67   388.7 1561.17   403.3 1563.86   428.2 1565.67   458.1 1569.58
   507.9 1570.97   532.8 1576.85   537.8 1580.95   542.7 1583.85   557.7 1588.06
   597.5 1603.56   607.5 1606.18   647.3 1606.66   657.3 1609.06   682.2 1607.53
#Mann= 3 , 0 , 0
       0      .1       0   373.7    .045       0   388.7      .1       0
#XS Ineff= 2 , 0
          338.53 1567.82
Permanent Ineff=
       F       F
Bank Sta=373.7,388.7
XS Rating Curve= 0 ,0
Exp/Cntr=0.3,0.1

Type RM Length L Ch R = 1 ,660.8   ,251.5,233.9,216
XS GIS Cut Line= 3
     1821106.925      246928.027     1821095.421       247298.21
     1821125.049      247561.271
#Sta/Elev= 30
       0 1620.31    19.8 1613.02    34.6 1609.02    69.1 1606.44   108.6 1604.89
   133.3 1601.34   143.2 1597.93     163 1587.86   177.8 1583.11   202.5 1577.64
     237 1572.05   256.8 1567.43     321 1562.77   340.7 1562.61   370.4 1563.55
   390.3 1563.14   405.3 1561.35   437.3 1554.78   450.3 1552.36   452.3 1552.85
   490.2  1564.7   500.2  1571.5   520.2  1583.1   525.2 1586.89   530.2 1589.27
   570.2 1599.98   580.1 1604.07   615.1 1620.64   625.1 1620.55   635.1 1623.38
#Mann= 3 , 0 , 0
       0      .1       0   437.3    .045       0   452.3      .1       0
Bank Sta=437.3,452.3
XS Rating Curve= 0 ,0
Exp/Cntr=0.3,0.1

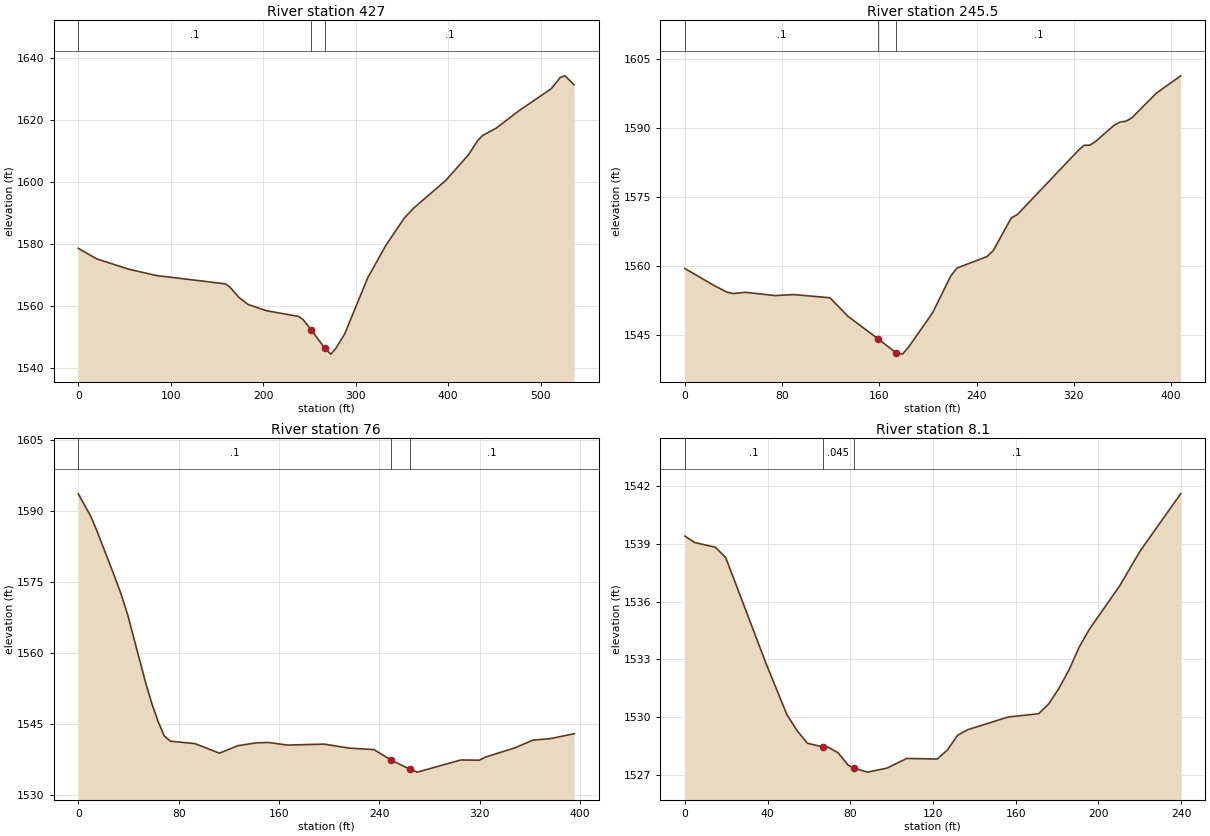
Type RM Length L Ch R = 1 ,427     ,191.1,181.4,171.8
XS GIS Cut Line= 2
     1820687.854      247289.451     1821118.425      247609.227
#Sta/Elev= 30
       0 1578.53    19.9 1575.14    54.6 1571.81    84.4 1569.77   158.9  1567.1
   163.9 1566.08   173.8  1562.7   183.7 1560.44   203.6 1558.43   238.4 1556.58
   243.3 1555.52   251.8 1552.32   266.8 1546.26   273.1 1544.44   278.1 1546.12
     288 1550.89   312.9 1568.97   332.7 1579.52   352.6 1588.31   362.5 1591.46
   397.3 1600.38   422.1 1608.72     432 1613.31     437 1614.87   451.9 1617.26
   476.7  1622.9   511.5 1629.99   521.4 1633.65   526.4 1634.14   536.3 1631.23
#Mann= 3 , 0 , 0
       0      .1       0   251.8    .045       0   266.8      .1       0
Bank Sta=251.8,266.8
XS Rating Curve= 0 ,0
Exp/Cntr=0.3,0.1

Type RM Length L Ch R = 1 ,245.5   ,176.6,169.6,162.5
XS GIS Cut Line= 2
     1820682.511      247580.961     1821081.062      247667.579
#Sta/Elev= 30
       0 1559.37    24.9 1555.55    34.8 1554.22    39.8 1553.92    49.7 1554.19
    74.6 1553.47    89.5  1553.7   119.4    1553   134.3 1548.96   159.1 1544.04
   174.1 1540.98   179.1 1540.74     184 1542.23   203.9 1549.75   218.8 1557.74
   223.8 1559.44   248.7 1561.98   253.7 1563.24   268.6 1570.37   273.6  1571.1
   323.3 1584.94   328.3 1586.16   333.2  1586.2   338.2 1587.06   353.1 1590.52
   358.1 1591.24   363.1 1591.41   368.1 1592.22     388 1597.52   407.9 1601.28
#Mann= 3 , 0 , 0
       0      .1       0   159.1    .045       0   174.1      .1       0
Bank Sta=159.1,174.1
XS Rating Curve= 0 ,0
Exp/Cntr=0.3,0.1

Type RM Length L Ch R = 1 ,76      ,60,67.9,64.5
XS GIS Cut Line= 4
      1820557.41      247821.189      1820710.77      247789.593
     1820878.056      247773.403     1820948.134      247764.206
#Sta/Elev= 30
       0 1593.59     9.8 1588.91    14.7 1585.84    29.4 1575.77    34.2  1572.3
    39.2 1568.16    53.8 1553.52    58.7 1549.17    63.6 1545.47    68.5 1542.41
    73.4  1541.3      93 1540.79   112.5 1538.77   127.2 1540.35   141.9 1540.95
   151.7 1541.03   166.5 1540.48   196.1 1540.68   215.9 1539.84   235.7 1539.52
   249.6 1537.29   264.6 1535.33   270.3 1534.76   304.9 1537.33   319.7 1537.28
   324.6 1537.94   348.2 1539.91   362.3 1541.52   376.5 1541.85   395.3 1542.88
#Mann= 3 , 0 , 0
       0      .1       0   249.6    .045       0   264.6      .1       0
Bank Sta=249.6,264.6
XS Rating Curve= 0 ,0
Exp/Cntr=0.3,0.1

Type RM Length L Ch R = 1 ,8.1     ,11.6,8.1,15.9
XS GIS Cut Line= 4
     1820734.578      247828.848     1820811.066      247848.816
     1820833.064      247840.694     1820950.503      247769.621
#Sta/Elev= 30
       0  1539.4     4.9 1539.06    14.8 1538.82    19.8 1538.28    39.5 1532.73
    49.4 1530.13    54.4 1529.29    59.3 1528.65    66.7 1528.46    69.2 1528.45
    74.1 1528.16      79 1527.51    81.7 1527.36    88.4 1527.15    97.8 1527.36
   107.4 1527.86   122.1 1527.83     127  1528.3   131.9 1529.06   136.8 1529.35
   156.4 1530.01   171.1 1530.18     176 1530.69   180.9 1531.49   185.8 1532.45
   190.8 1533.65   195.6 1534.55   210.4 1536.83   220.2 1538.62   239.8 1541.59
#Mann= 3 , 0 , 0
       0      .1       0    66.7    .045       0    81.7      .1       0
Bank Sta=66.7,81.7
XS Rating Curve= 0 ,0
Exp/Cntr=0.3,0.1

Chan Stop Cuts=-1
Use User Specified Reach Order=0